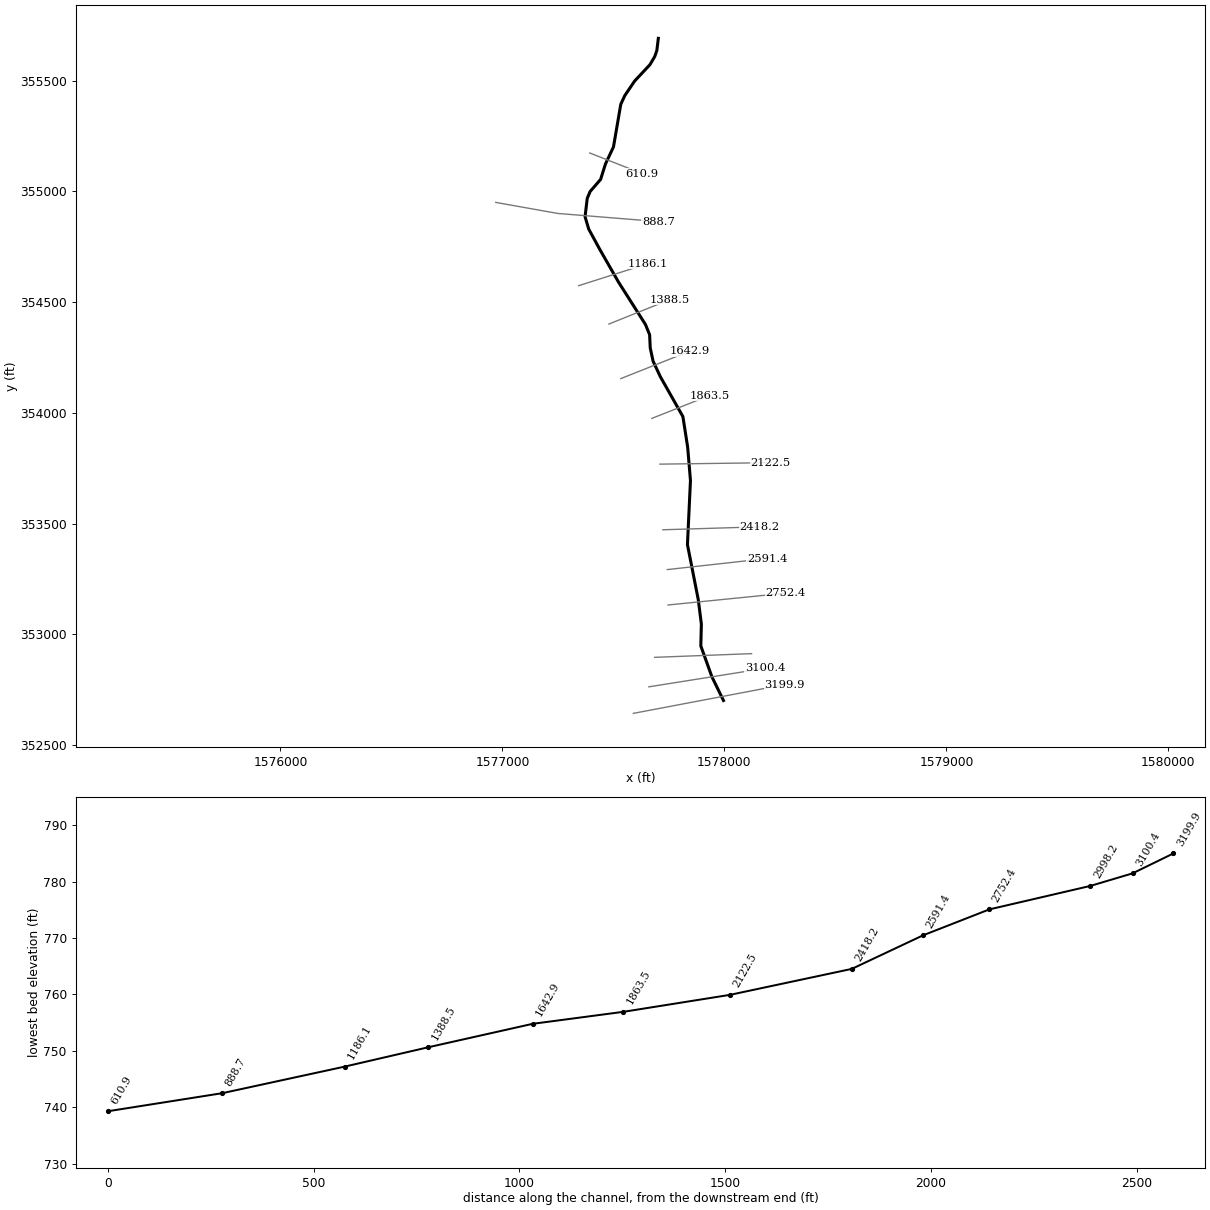
--- SPRUCEFK.prj (project) ---

Proj Title=SPRUCEFK
Current Plan=p01
Default Exp/Contr=0,0
English Units
Geom File=g01
Flow File=f01
Plan File=p01
BEGIN DESCRIPTION:
END DESCRIPTION:
DSS Export Rating Curves= 0
DSS Export Rating Curve Sorted= 0
DSS Export Volume Flow Curves= 0
DXF OffsetX= 0
DXF OffsetY= 0
DXF ScaleX= 0
DXF ScaleY= 0

--- SPRUCEFK.p01 (plan) ---

Plan Title=Floodplain
Program Version=4.00
Geom File=g01
Flow File=f01
K Sum by GR=0
Std Step Tol=0.01
Critical Tol=0.01
Num of Std Step Trials=20
Max Error Tol=0.3
Flow Tol Ratio=0.001
Split Flow NTrial=30
Split Flow Tol=0.02
Split Flow Ratio=0.02
Log Output Level=0
Friction Slope Method=1
Unsteady Friction Slope Method=2
Unsteady Bridges Friction Slope Method=1
Global Log Level=0
CheckData=False
Run HTab=0
Run UNet=0
Run PostProcess=0
UNET Theta=0
UNET Theta Warmup=0
UNET ZTol=0
UNET ZSATol=0
UNET MxIter=0
UNET MaxInSteps=0
UNET DtIC=0
UNET DtMin=0
UNET MaxCRTS=0
UNET WFStab=0
UNET SFStab=0
UNET WFX=0
UNET SFX=0
UNET DSS MLevel=0
UNET DZMax Abort=0
UNET Convert EG Bridges=0
UNET Use Existing IB Tables=0
UNET Froude Limit=0
UNET Froude Power=0
Write IC File=0
Echo Input=False
Echo Output=False
Write Detailed=0

--- SPRUCEFK.f01 (steady flow) ---

Flow Title=NFF Regression Equation
Program Version=4.00
Number of Profiles=1
Profile Names=P100yr
River Rch & RM=SPRUCEFK,Main      ,3199.9
     355
River Rch & RM=SPRUCEFK,Main      ,1186.1
386.5370
River Rch & RM=SPRUCEFK,Main      ,888.7
545.0750
Boundary for River Rch & Prof#=SPRUCEFK,Main      ,1
Up Type=0
Dn Type=3
Dn Slope=0.01475

--- SPRUCEFK.g01 (geometry) ---

Geom Title=Geometry
Program Version=4.00

River Reach=SPRUCEFK        ,Main
Reach XY= 30
     1577995.678      352702.109     1577943.585      352809.343
     1577893.785      352948.352     1577896.249      353046.986
     1577882.434      353156.591     1577833.517      353405.735
     1577847.147      353695.299     1577834.497       353845.84
     1577813.019       353983.66     1577710.994      354164.402
     1577678.647      354233.995     1577665.905      354293.787
     1577663.185      354353.012     1577644.415      354399.349
     1577523.049      354590.562     1577439.644      354736.466
     1577388.757      354830.032     1577372.342      354885.843
     1577382.084      354968.331     1577395.002      354999.336
      1577442.41      355054.267     1577464.266      355123.861
     1577500.379      355201.011     1577533.209      355393.067
     1577551.266      355432.463     1577595.587      355498.123
     1577664.529      355571.991     1577685.869      355608.104
     1577695.718       355636.01     1577702.361      355690.916

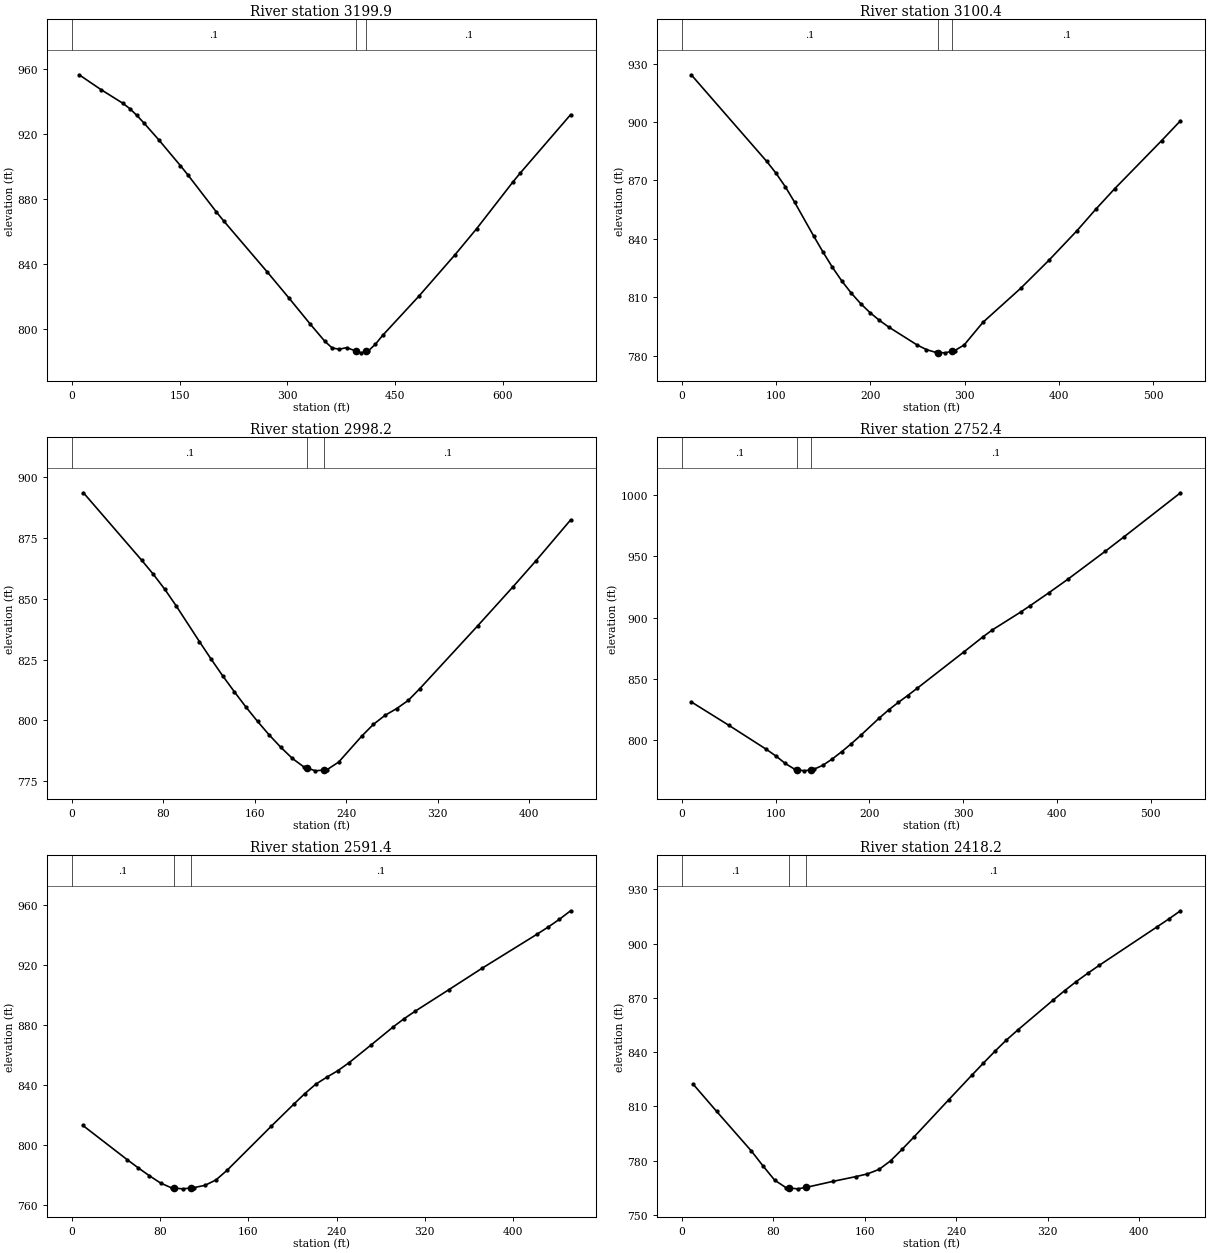
Type RM Length L Ch R = 1 ,3199.9  ,100,99.4,98.7
XS GIS Cut Line= 2
     1577589.732       352643.95     1578272.041      352773.755
#Sta/Elev= 30
    10.1  956.42    40.3  947.34    70.5  938.98    80.5  935.61    90.6  931.32
   100.7   926.5   120.8  916.41     151  900.46   161.1  894.93   201.3   871.8
   211.4  866.31   271.8  834.99     302  818.94   332.2  802.57   352.3   792.1
   362.4  788.03   372.4  787.23   382.5  788.21   395.1   786.2   402.6     785
   410.1  785.85   412.7  786.14   422.8  790.38   432.8  795.77   483.2  819.92
   533.5  845.45   563.7  861.56     614  890.23   624.1  895.68   694.5  931.81
#Mann= 3 , 0 , 0
       0      .1       0   395.1    .045       0   410.1      .1       0
Bank Sta=395.1,410.1
XS Rating Curve= 0 ,0
Exp/Cntr=0.3,0.1

Type RM Length L Ch R = 1 ,3100.4  ,105.1,102.2,99.4
XS GIS Cut Line= 2
     1577659.627       352763.77     1578182.176      352846.978
#Sta/Elev= 30
      10   924.3    89.9  879.91    99.8  873.84   109.8  866.79   119.8  858.74
   139.8  841.57   149.8  833.24   159.7  825.46   169.7  818.42   179.7   812.2
   189.7  806.77   199.7  802.11   209.7  798.13   219.6  794.69   249.6  785.52
   259.6  783.12   269.6  781.67     272  781.62   279.5  781.46     287  782.33
   289.5  782.62   299.5  785.47   319.5  797.13   359.4  814.54   389.4  828.96
   419.3  844.22   439.3  855.27   459.2  865.72   509.2  890.53   529.1  900.69
#Mann= 3 , 0 , 0
       0      .1       0     272    .045       0     287      .1       0
Bank Sta=272,287
XS Rating Curve= 0 ,0
Exp/Cntr=0.3,0.1

Type RM Length L Ch R = 1 ,2998.2  ,244.1,245.8,247.4
XS GIS Cut Line= 2
     1577686.254      352896.903     1578122.266      352913.545
#Sta/Elev= 30
    10.1  893.61    60.9  865.95      71  860.23    81.2  853.96    91.3  847.05
   111.6  832.38   121.8  825.19   131.9  818.34   142.1  811.78   152.2  805.52
   162.4  799.59   172.5  794.07   182.6  789.01   192.8  784.38   202.9  780.86
   205.6  780.43   213.1  779.24   220.6   779.6   223.2  779.72   233.4  782.85
   253.7  793.58   263.8  798.36     274  802.08   284.1  804.84   294.3  808.22
   304.4  813.05   355.2  838.98   385.6  854.77   405.9  865.59   436.3  882.43
#Mann= 3 , 0 , 0
       0      .1       0   205.6    .045       0   220.6      .1       0
Bank Sta=205.6,220.6
XS Rating Curve= 0 ,0
Exp/Cntr=0.3,0.1

Type RM Length L Ch R = 1 ,2752.4  ,160.9,161.1,161.3
XS GIS Cut Line= 2
     1577746.164      353133.215      1578275.37      353186.469
#Sta/Elev= 30
      10  831.36    50.2  812.21    90.3  792.55   100.4  787.15   110.4  781.09
   120.4  776.34     123  776.02   130.5  775.07     138  775.93   140.5  776.22
   150.5  779.62   160.6  784.82   170.6  790.72   180.6  797.08   190.7  803.94
   210.7  818.22   220.8  824.89   230.8  830.83   240.9   836.5   250.9  842.34
   301.1  872.24   321.1  884.33   331.2  890.04   361.3  904.54   371.3  909.69
   391.4  920.29   411.5  931.25   451.6  954.18   471.7  966.01   531.9 1001.94
#Mann= 3 , 0 , 0
       0      .1       0     123    .045       0     138      .1       0
Bank Sta=123,138
XS Rating Curve= 0 ,0
Exp/Cntr=0.3,0.1

Type RM Length L Ch R = 1 ,2591.4  ,175,173.1,171.3
XS GIS Cut Line= 2
     1577742.836      353292.975     1578192.161        353342.9
#Sta/Elev= 30
      10  812.76    50.2   789.9    60.3   784.4    70.3  779.18    80.4  774.32
    90.4  771.11      93  770.95   100.5  770.47     108  771.07   110.5  771.27
   120.6   772.8   130.6   776.4   140.7  782.88   180.8  812.33   200.9  826.81
     211  833.93     221  840.31   231.1  845.02   241.1  849.36   251.2  854.65
   271.3  866.57   291.3   878.6   301.4  884.18   311.4  889.16   341.6  903.37
   371.7  917.67     422  940.62     432  945.36     442  950.44   452.1  956.12
#Mann= 3 , 0 , 0
       0      .1       0      93    .045       0     108      .1       0
Bank Sta=93,108
XS Rating Curve= 0 ,0
Exp/Cntr=0.3,0.1

Type RM Length L Ch R = 1 ,2418.2  ,296.1,295.7,295.3
XS GIS Cut Line= 2
     1577722.866      353472.705     1578158.878      353486.019
#Sta/Elev= 30
    10.1  822.19    30.4  807.34    60.9  785.38      71   777.2    81.2  769.32
    91.3  765.11    93.9  764.96   101.4  764.52   108.9  765.35   131.9   768.6
   152.2  771.27   162.3  772.75   172.5  775.25   182.6  779.98   192.7  786.36
   202.9  793.04   233.3   813.6   253.6  827.23   263.8  833.95   273.9  840.52
     284  846.75   294.2  852.42   324.6  868.66   334.8  873.93   344.9  878.93
   355.1  883.58   365.2  887.99   415.9  909.29   426.1  913.62   436.2  918.09
#Mann= 3 , 0 , 0
       0      .1       0    93.9    .045       0   108.9      .1       0
Bank Sta=93.9,108.9
XS Rating Curve= 0 ,0
Exp/Cntr=0.3,0.1

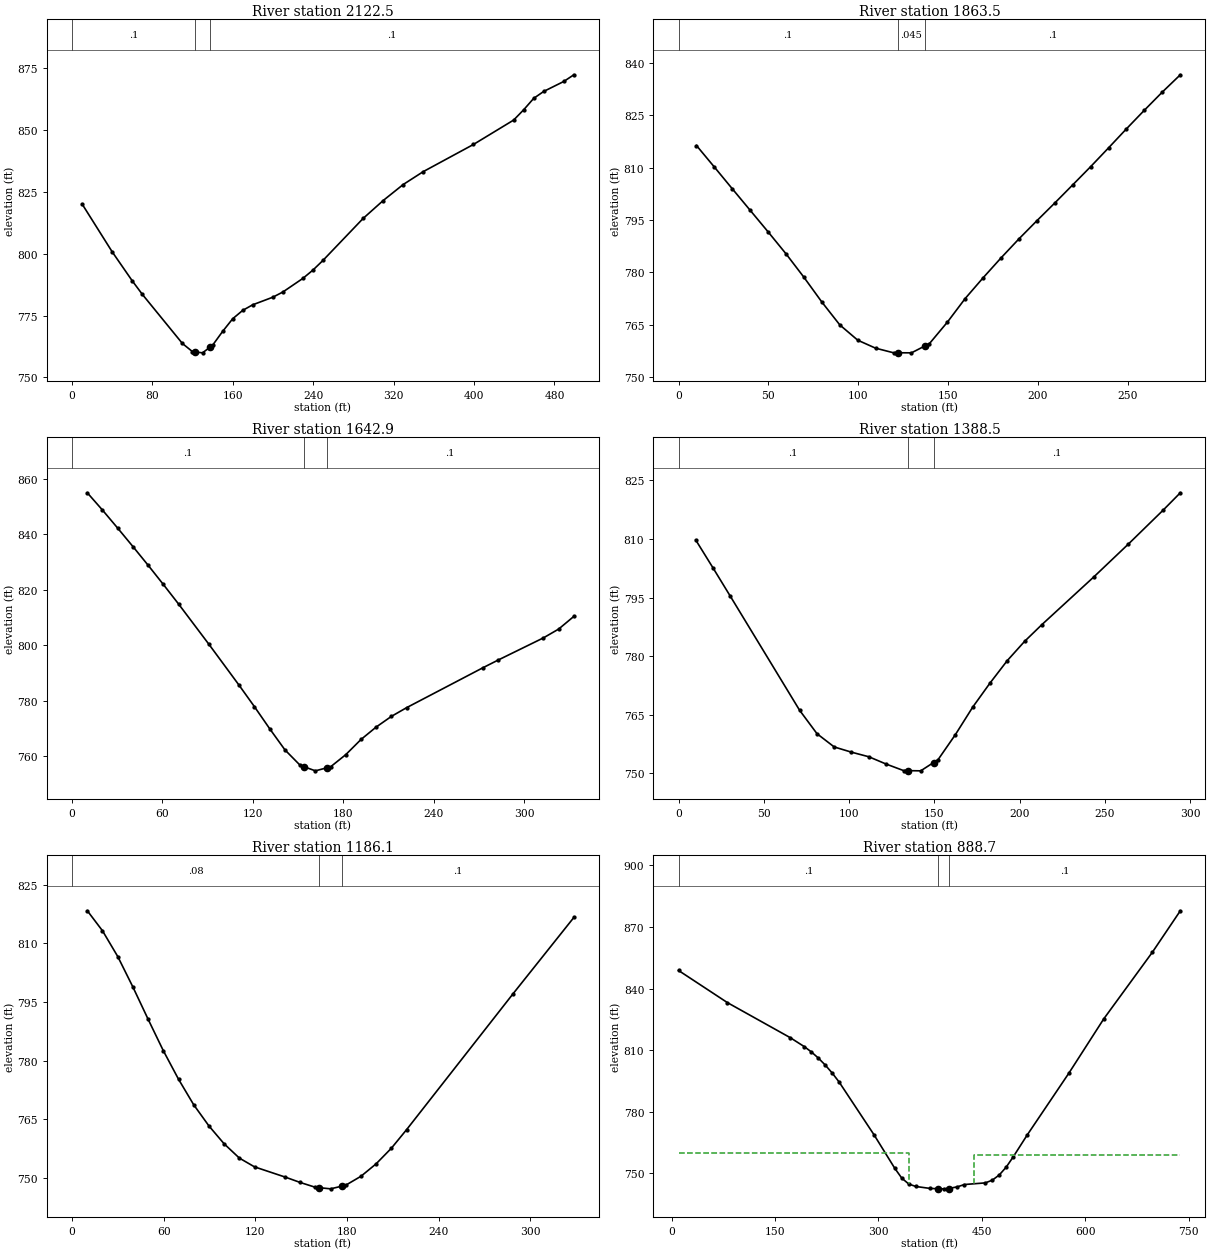
Type RM Length L Ch R = 1 ,2122.5  ,250.9,259.1,267.3
XS GIS Cut Line= 2
     1577709.552      353768.927     1578208.803      353775.584
#Sta/Elev= 30
      10  820.12    39.9   800.8    59.9  789.04    69.9  783.59   109.8   763.7
   119.8  760.41   122.3  760.29   129.8  759.92   137.3  762.22   139.8  762.98
   149.8  768.58   159.8   773.7   169.8   777.1   179.7  779.35   199.7  782.42
   209.7  784.52   229.7  790.05   239.7  793.41   249.6  797.29   289.6  814.29
   309.6  821.55   329.5  828.02   349.5  833.25   399.4  844.23   439.4   854.1
   449.4  858.27   459.4   862.9   469.3  865.68   489.3  869.72   499.3  872.42
#Mann= 3 , 0 , 0
       0      .1       0   122.3    .045       0   137.3      .1       0
Bank Sta=122.3,137.3
XS Rating Curve= 0 ,0
Exp/Cntr=0.3,0.1

Type RM Length L Ch R = 1 ,1863.5  ,220.5,220.6,220.6
XS GIS Cut Line= 2
     1577672.941      353975.284     1577932.551      354078.463
#Sta/Elev= 30
      10  816.31      20  810.12    29.9  803.94    39.9  797.75    49.9  791.56
    59.9  785.25    69.8  778.58    79.8  771.47    89.8  764.91    99.8  760.53
   109.7  758.25   119.7  756.93   122.2  756.93   129.7  756.91   137.2  758.89
   139.7  759.55   149.7  765.71   159.6  772.47   169.6  778.42   179.6  784.13
   189.6   789.6   199.5  794.75   209.5  799.85   219.5  805.05   229.5  810.28
   239.5  815.68   249.4   821.1   259.4  826.44   269.4  831.65   279.4  836.59
#Mann= 3 , 0 , 0
       0      .1       0   122.2    .045       0   137.2      .1       0
Bank Sta=122.2,137.2
XS Rating Curve= 0 ,0
Exp/Cntr=0.3,0.1

Type RM Length L Ch R = 1 ,1642.9  ,254.4,254.4,254.4
XS GIS Cut Line= 2
     1577533.151      354155.014     1577842.686      354278.163
#Sta/Elev= 27
    10.1  854.97    20.2  848.73    30.3  842.22    40.4  835.59    50.5  828.85
    60.6  821.93    70.7  814.89    90.9  800.34     111  785.53   121.1  777.87
   131.2  769.94   141.3  762.34   151.4  756.78     154  756.26   161.5  754.78
     169  755.85   171.6  756.23   181.7  760.62   191.8  766.08   201.9  770.57
     212  774.41   222.1  777.55   272.6  791.89   282.7  794.66   312.9  802.69
     323  805.86   333.1  810.43
#Mann= 3 , 0 , 0
       0      .1       0     154    .045       0     169      .1       0
Bank Sta=154,169
XS Rating Curve= 0 ,0
Exp/Cntr=0.3,0.1

Type RM Length L Ch R = 1 ,1388.5  ,204.1,202.4,200.8
XS GIS Cut Line= 2
     1577479.897      354401.311     1577752.821      354511.147
#Sta/Elev= 24
    10.1  809.71    20.3  802.52    30.4   795.3      71  766.11    81.2  760.11
    91.3  756.72   101.4  755.39   111.6  754.21   121.7  752.35   131.9  750.68
   134.5  750.66     142  750.61   149.5  752.73   152.2   753.5   162.3  759.87
   172.5  766.94   182.6  773.08   192.7  778.82   202.9  783.77     213  788.04
   243.5  800.28   263.8  808.71   284.1  817.36   294.2  821.82
#Mann= 3 , 0 , 0
       0      .1       0   134.5    .045       0   149.5      .1       0
Bank Sta=134.5,149.5
XS Rating Curve= 0 ,0
Exp/Cntr=0.3,0.1

Type RM Length L Ch R = 1 ,1186.1  ,306.2,297.4,288.5
XS GIS Cut Line= 2
     1577343.435      354574.385     1577656.299      354674.235
#Sta/Elev= 25
      10  818.29    19.9  813.18    29.9  806.59    39.8  798.81    49.8  790.53
    59.7  782.53    69.7   775.2    79.6  768.69    89.6  763.26    99.5  758.71
   109.5  755.05   119.4  752.81   139.3  750.22   149.3  748.82   159.2  747.59
   161.7  747.49   169.2  747.19   176.7  747.89   179.1  748.12   189.1  750.41
     199  753.59     209  757.59   218.9  762.31   288.6  797.07   328.4  816.58
#Mann= 3 , 0 , 0
       0     .08       0   161.7    .045       0   176.7      .1       0
Bank Sta=161.7,176.7
XS Rating Curve= 0 ,0
Exp/Cntr=0.3,0.1

Type RM Length L Ch R = 1 ,888.7   ,284.2,277.8,271.4
XS GIS Cut Line= 3
     1576970.274      354950.304     1577249.324      354900.524
     1577702.508      354863.767
#Sta/Elev= 30
    10.1  848.82      81  833.17   172.1  816.11   192.3  811.79   202.5  809.24
   212.6  806.27   222.7  802.85   232.8  798.98     243  794.54   293.6  768.86
   323.9  752.44     334  747.69   344.1  744.83   354.2  743.64   374.4  742.71
   387.1   742.5   394.6  742.48   402.1  742.63   414.8  743.48   424.9  744.58
   455.2  745.38   465.3   746.7   475.4  749.23   485.5  753.06   495.6  758.02
   515.8  768.63   576.5  798.86     627  825.24   697.7  857.78   738.1  877.89
#Mann= 3 , 0 , 0
    10.1      .1       0   387.1    .045       0   402.1      .1       0
#XS Ineff= 2 , 0
          344.97  760.15  438.93          759.11
Permanent Ineff=
       F       F
Bank Sta=387.1,402.1
XS Rating Curve= 0 ,0
Exp/Cntr=0.3,0.1

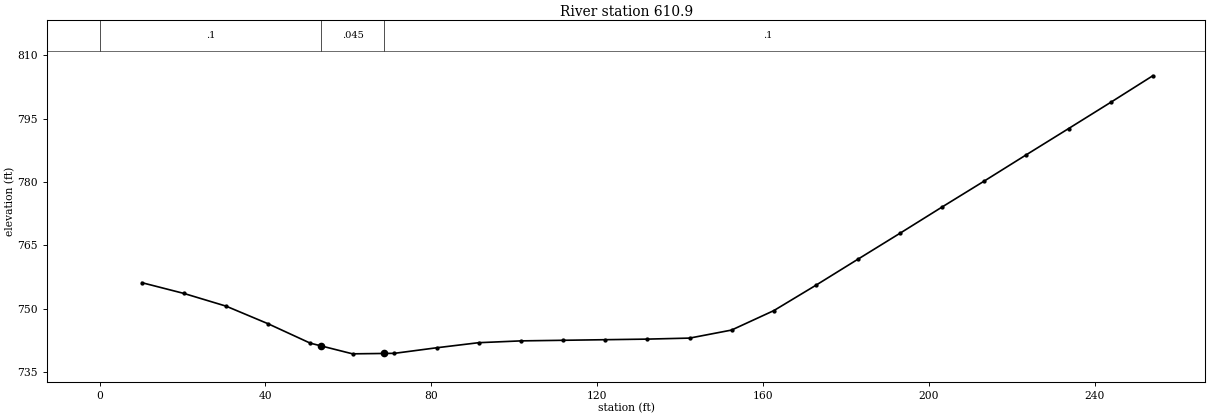
Type RM Length L Ch R = 1 ,610.9   ,605.1,610.9,616.7
XS GIS Cut Line= 2
      1577393.36      355173.485     1577629.672      355080.292
#Sta/Elev= 27
    10.2  756.14    20.3   753.6    30.5  750.58    40.6  746.42    50.8  741.81
    53.5  741.14      61  739.28    68.5  739.37    71.1   739.4    81.3  740.72
    91.4  741.92   101.6  742.35   111.8  742.49   121.9  742.63   132.1  742.77
   142.3  743.01   152.4  744.91   162.6  749.52   172.7   755.5   182.9  761.71
   193.1  767.89   203.2  774.08   213.4  780.25   223.5  786.45   233.7  792.66
   243.9   798.9     254  805.17
#Mann= 3 , 0 , 0
       0      .1       0    53.5    .045       0    68.5      .1       0
Bank Sta=53.5,68.5
XS Rating Curve= 0 ,0
Exp/Cntr=0.3,0.1

Chan Stop Cuts=-1
Use User Specified Reach Order=0